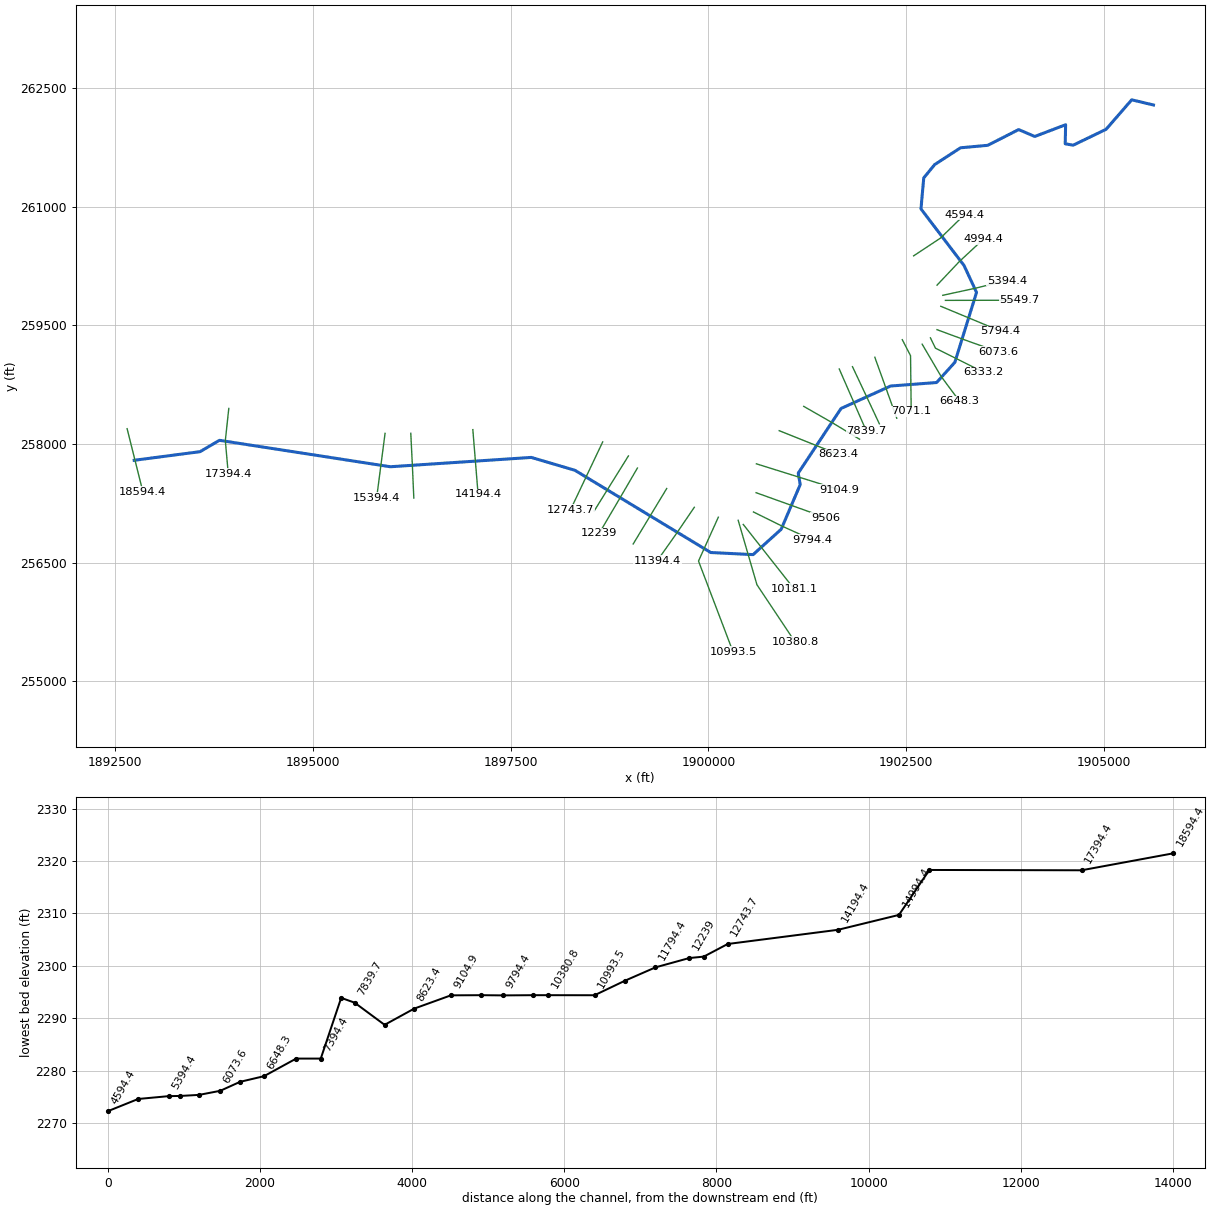
--- SkCrk.prj (project) ---

Proj Title=SkCrk
Current Plan=p01
Default Exp/Contr=0,0
English Units
Geom File=g01
Flow File=f01
Plan File=p01
BEGIN DESCRIPTION:
END DESCRIPTION:
DSS Export Rating Curves= 0
DSS Export Rating Curve Sorted= 0
DSS Export Volume Flow Curves= 0
DXF OffsetX= 0
DXF OffsetY= 0
DXF ScaleX= 0
DXF ScaleY= 0

--- SkCrk.p01 (plan) ---

Plan Title=Floodplain
Program Version=4.00
Geom File=g01
Flow File=f01
K Sum by GR=0
Std Step Tol=0.01
Critical Tol=0.01
Num of Std Step Trials=20
Max Error Tol=0.3
Flow Tol Ratio=0.001
Split Flow NTrial=30
Split Flow Tol=0.02
Split Flow Ratio=0.02
Log Output Level=0
Friction Slope Method=1
Unsteady Friction Slope Method=2
Unsteady Bridges Friction Slope Method=1
Global Log Level=0
CheckData=False
Run HTab=0
Run UNet=0
Run PostProcess=0
UNET Theta=0
UNET Theta Warmup=0
UNET ZTol=0
UNET ZSATol=0
UNET MxIter=0
UNET MaxInSteps=0
UNET DtIC=0
UNET DtMin=0
UNET MaxCRTS=0
UNET WFStab=0
UNET SFStab=0
UNET WFX=0
UNET SFX=0
UNET DSS MLevel=0
UNET DZMax Abort=0
UNET Convert EG Bridges=0
UNET Use Existing IB Tables=0
UNET Froude Limit=0
UNET Froude Power=0
Write IC File=0
Echo Input=False
Echo Output=False
Write Detailed=0

--- SkCrk.f01 (steady flow) ---

Flow Title=NFF Regression Equation
Program Version=4.10
Number of Profiles= 1
Profile Names=P100yr
River Rch & RM=SkCrk,Main            ,18594.4
535.6406
River Rch & RM=SkCrk,Main            ,17394.4
558.0776
River Rch & RM=SkCrk,Main            ,14994.4
717.1494
River Rch & RM=SkCrk,Main            ,14994.4
616.1918
River Rch & RM=SkCrk,Main            ,14194.4
728.5631
River Rch & RM=SkCrk,Main            ,12429.2
     855
River Rch & RM=SkCrk,Main            ,10380.8
 867.775
River Rch & RM=SkCrk,Main            ,6648.3
 925.458
River Rch & RM=SkCrk,Main            ,6333.2
1034.766
River Rch & RM=SkCrk,Main            ,3394.4
1098.627
River Rch & RM=SkCrk,Main            ,280
1183.486
Boundary for River Rch & Prof#=SkCrk,Main            , 1
Up Type= 0
Dn Type= 3
Dn Slope=0.002121
DSS Import GetInterval= 0
DSS Import GetPeak= 0
DSS Import FillOption= 0

--- SkCrk.g01 (geometry) ---

Geom Title=USGS 3m DEM
Program Version=4.10

River Reach=SkCrk           ,Main
Reach XY= 30
     1892738.478      257794.625     1893571.811         257904.
     1893816.603      258047.229     1895978.192      257713.208
     1897760.613      257831.083     1898312.696      257668.323
     1900030.144      256629.261     1900566.029      256602.798
     1900920.791      256922.821     1901162.043      257488.144
     1901136.291      257631.973     1901678.152      258449.781
     1902304.884      258733.427     1902886.915      258777.698
     1903117.384      259032.906     1903391.799      259916.841
     1903233.269      260256.865     1902688.999      260971.708
     1902724.155      261363.636     1902862.175      261531.604
     1903188.999      261743.844      1903533.59      261775.305
     1903924.676      261974.313     1904127.801      261887.073
     1904518.412      262035.401     1904513.217      261794.625
        1904614.      261776.933     1905030.494      261977.963
     1905354.363      262350.615     1905629.378      262284.823

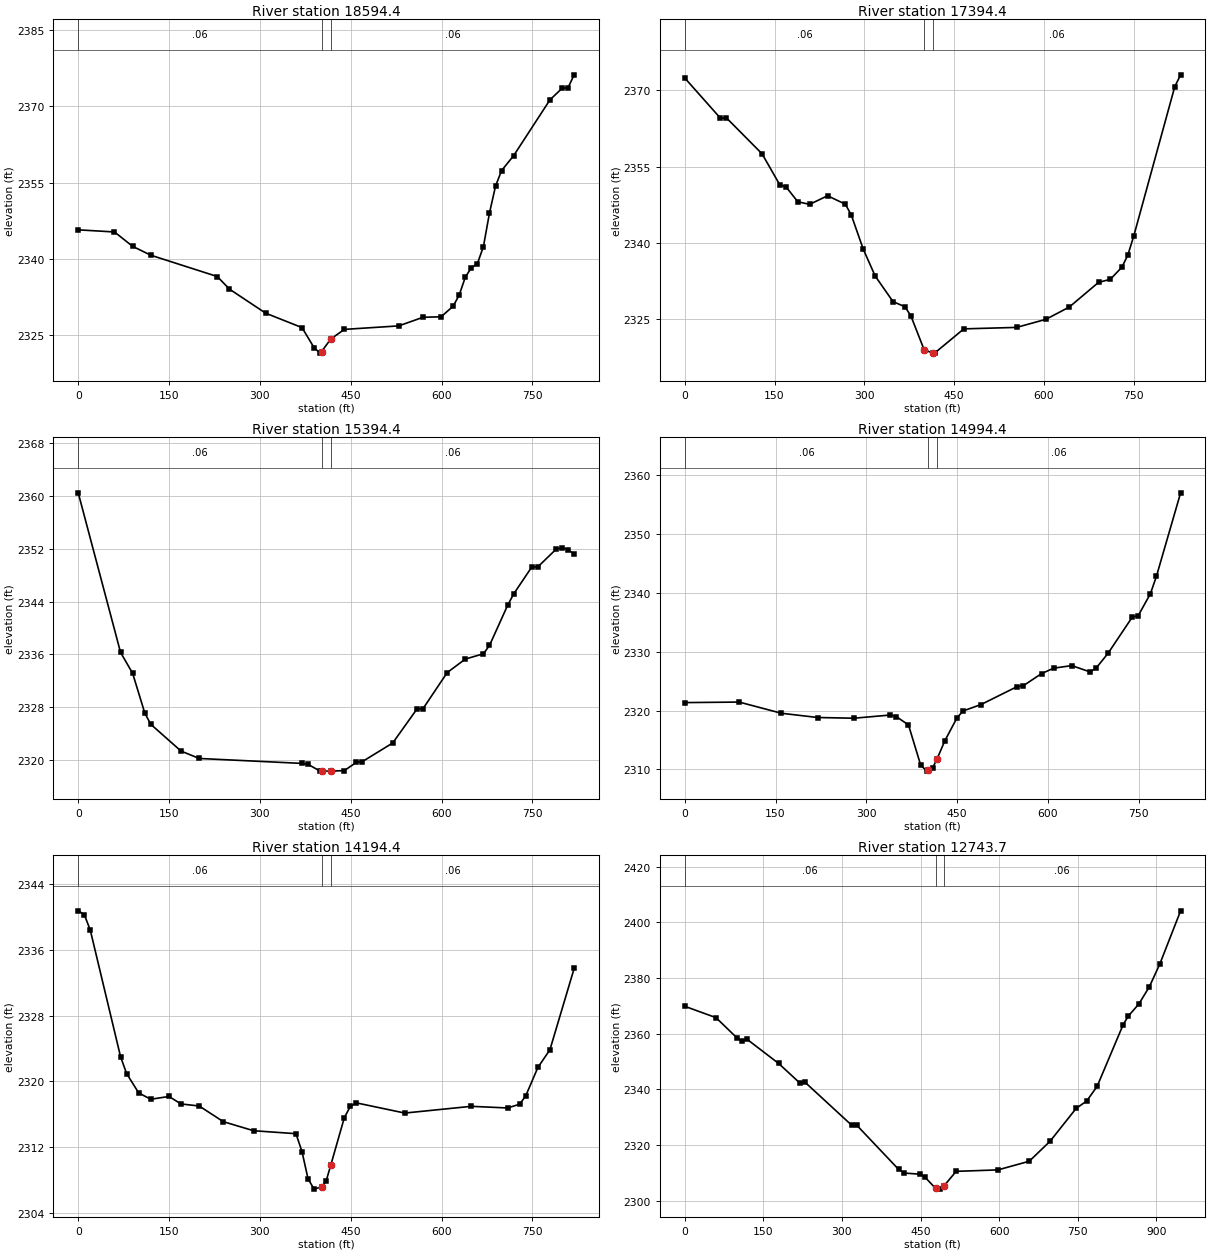
Type RM Length L Ch R = 1 ,18594.4 ,1207.5,1199.7,1196.3
XS GIS Cut Line= 3
      1892648.86      258194.324     1892748.179      257797.051
     1892847.498      257399.777
#Sta/Elev= 30
       0 2345.72    59.9  2345.3    89.9 2342.47   119.8 2340.73   229.7 2336.53
   249.7 2334.06   309.6 2329.32   369.6 2326.48   389.5 2322.53   399.5 2321.46
     402 2321.78     417 2324.23   439.5 2326.13   529.4 2326.82   569.3 2328.51
   599.3 2328.61   619.2  2330.7   629.2  2332.9   639.2 2336.39   649.2 2338.27
   659.2 2339.06   669.2 2342.44   679.2 2349.06   689.2 2354.34   699.2 2357.39
   719.1 2360.32     779 2371.29     799 2373.57     809 2373.71     819 2376.22
#Mann= 3 , 0 , 0
       0     .06       0     402    .045       0     417     .06       0
Bank Sta=402,417
XS Rating Curve= 0 ,0
Exp/Cntr=0.3,0.1

Type RM Length L Ch R = 1 ,17394.4 ,2000.5,2000,1995
XS GIS Cut Line= 3
     1893934.861      258450.092     1893891.059      258044.916
     1893928.014      257625.915
#Sta/Elev= 30
       0 2372.47    59.6 2364.55    69.6 2364.61   129.2 2357.52     159 2351.37
     169 2351.05   188.9 2348.06   208.7 2347.56   238.6 2349.25   268.4 2347.58
   278.3 2345.43   298.2 2338.73   318.1 2333.44   347.9 2328.39   367.8 2327.38
   377.7 2325.59     400 2318.87     415 2318.25   417.3 2318.24   466.2 2323.02
   554.3 2323.31   603.2  2324.9   642.3 2327.32   691.2 2332.19   710.8 2332.78
   730.3  2335.2   740.1 2337.58   749.9  2341.3   818.4 2370.74   828.2 2373.08
#Mann= 3 , 0 , 0
       0     .06       0     400    .045       0     415     .06       0
Bank Sta=400,415
XS Rating Curve= 0 ,0
Exp/Cntr=0.3,0.1

Type RM Length L Ch R = 1 ,15394.4 ,396,400,403.9
XS GIS Cut Line= 3
     1895911.133      258134.927     1895858.157      257728.868
      1895805.18      257322.809
#Sta/Elev= 30
       0 2360.48    69.9  2336.3    89.9 2333.12   109.9 2327.11   119.8  2325.4
   169.8 2321.34   199.8 2320.22   369.6 2319.47   379.5 2319.33   399.5  2318.3
     402  2318.3     417  2318.3   439.5 2318.38   459.4 2319.64   469.4 2319.75
   519.4 2322.57   559.3  2327.7   569.3 2327.75   609.3 2333.23   639.2 2335.28
   669.2 2336.09   679.2 2337.35   709.1 2343.42   719.1 2345.15   749.1 2349.25
   759.1 2349.26     789 2351.92     799 2352.17     809 2351.89     819 2351.16
#Mann= 3 , 0 , 0
       0     .06       0     402    .045       0     417     .06       0
Bank Sta=402,417
XS Rating Curve= 0 ,0
Exp/Cntr=0.3,0.1

Type RM Length L Ch R = 1 ,14994.4 ,799.3,800,800.8
XS GIS Cut Line= 3
     1896236.544      258136.002     1896256.798      257727.004
     1896274.844      257317.895
#Sta/Elev= 30
       0 2321.35    89.9 2321.44   159.8 2319.54   219.7 2318.82   279.7  2318.7
   339.6 2319.24   349.6 2318.96   369.6 2317.56   389.5 2310.82   399.5 2309.72
     402 2309.86   409.5 2310.28     417 2311.84   429.5 2314.85   449.4  2318.7
   459.4 2319.92   489.4 2321.02   549.3 2324.08   559.3 2324.22   589.3 2326.27
   609.3 2327.19   639.2 2327.63   669.2 2326.57   679.2 2327.17   699.2 2329.72
   739.1 2335.85   749.1 2336.12   769.1 2339.83     779 2342.77     819 2356.95
#Mann= 3 , 0 , 0
       0     .06       0     402    .045       0     417     .06       0
Bank Sta=402,417
XS Rating Curve= 0 ,0
Exp/Cntr=0.3,0.1

Type RM Length L Ch R = 1 ,14194.4 ,1462.5,1450.7,1438.9
XS GIS Cut Line= 3
     1897021.326      258182.293     1897054.547      257774.143
     1897087.768      257365.993
#Sta/Elev= 30
       0 2340.76      10 2340.31      20 2338.39    69.9 2323.01    79.9 2320.95
    99.9 2318.59   119.8 2317.82   149.8 2318.16   169.8 2317.25   199.8    2317
   239.7 2315.09   289.6 2313.99   359.6 2313.63   369.6 2311.44   379.5 2308.14
   389.5 2306.88     402 2307.15   409.5 2307.89     417 2309.78   439.5 2315.59
   449.4 2316.95   459.4 2317.38   539.3 2316.14   649.2 2316.96   709.1 2316.76
   729.1 2317.22   739.1 2318.25   759.1 2321.69     779 2323.85     819 2333.75
#Mann= 3 , 0 , 0
       0     .06       0     402    .045       0     417     .06       0
Bank Sta=402,417
XS Rating Curve= 0 ,0
Exp/Cntr=0.3,0.1

Type RM Length L Ch R = 1 ,12743.7 ,317.1,314.6,312
XS GIS Cut Line= 2
     1898663.711       258027.25      1898258.07      257172.506
#Sta/Elev= 30
       0 2369.88    59.8 2365.78    99.6 2358.54   109.6 2357.37   119.5 2357.94
   179.3 2349.32   219.1  2342.4   229.1 2342.66   318.7 2327.11   328.6 2327.07
   408.3 2311.23   418.3 2309.95   448.2 2309.55   458.1 2308.52   478.8 2304.41
     488 2304.17   493.8 2305.13   517.9 2310.56   597.6 2311.08   657.3 2314.19
   697.1 2321.38   746.9  2333.2   766.8  2335.8   786.8 2341.09   836.6 2363.32
   846.5 2366.39   866.4 2370.69   886.4 2376.86   906.3 2385.01   946.1 2404.17
#Mann= 3 , 0 , 0
       0     .06       0   478.8    .045       0   493.8     .06       0
Bank Sta=478.8,493.8
XS Rating Curve= 0 ,0
Exp/Cntr=0.3,0.1

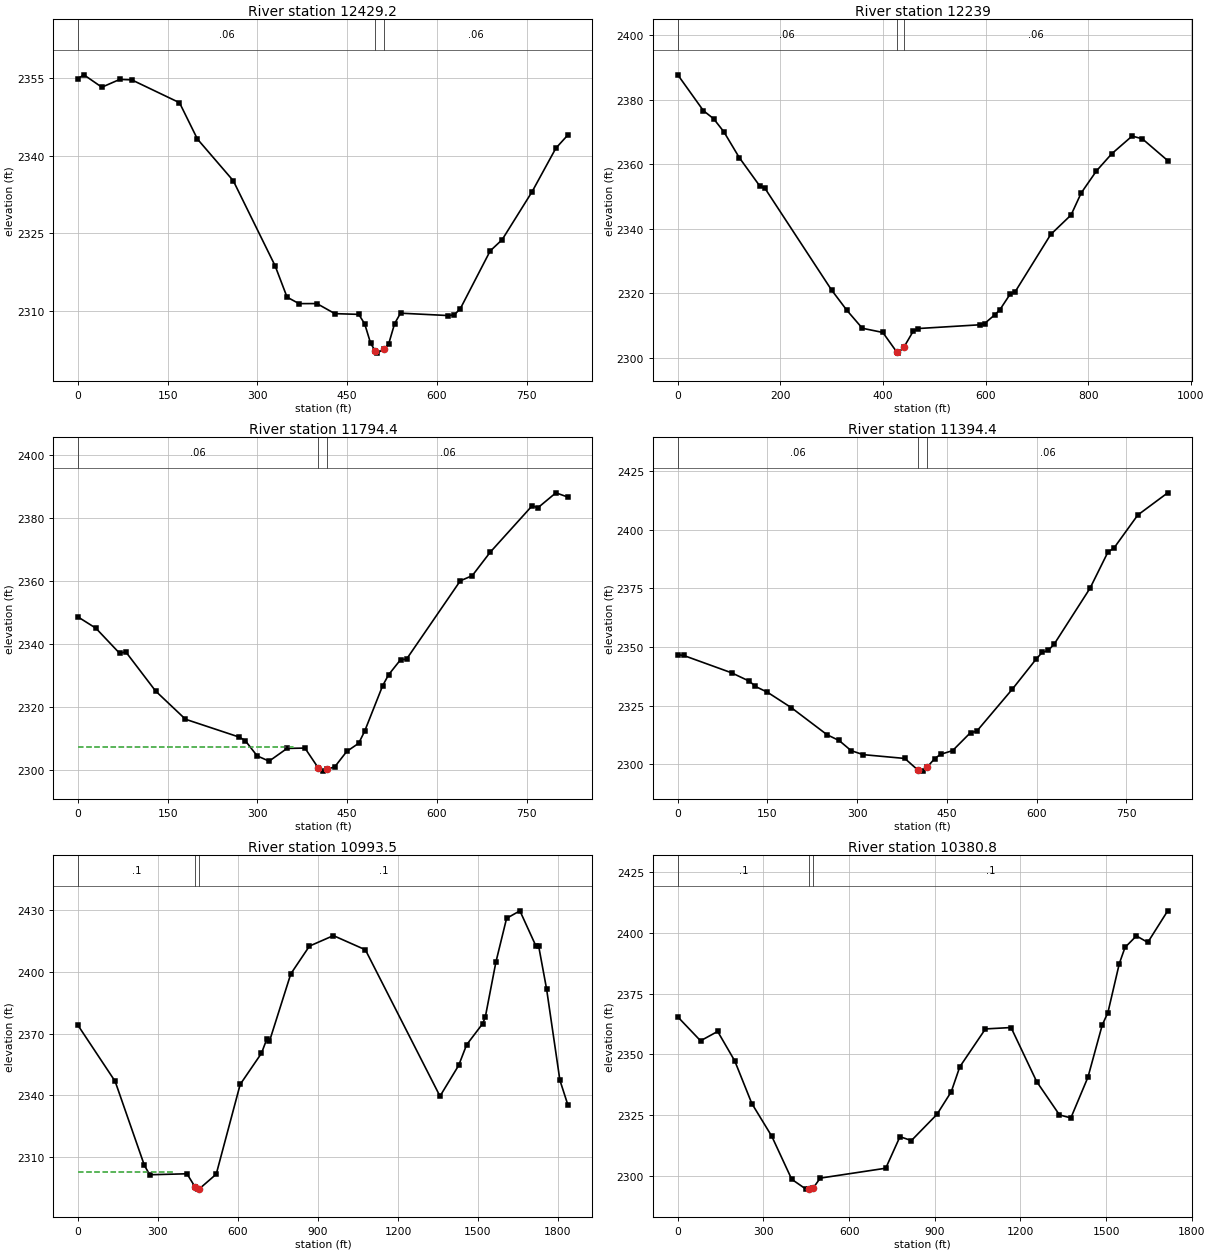
Type RM Length L Ch R = 1 ,12429.2 ,189.7,190.2,190.8
XS GIS Cut Line= 2
     1898988.863      257849.856     1898555.909      257154.649
#Sta/Elev= 30
       0 2354.94      10 2355.68      40 2353.28    69.9 2354.79    89.9 2354.71
   169.8 2350.28   199.8 2343.23   259.7 2335.16   329.6 2318.69   349.6 2312.61
   369.6 2311.35   399.5 2311.36   429.5 2309.41   469.4 2309.27   479.4 2307.43
   489.4 2303.63   496.9 2302.23   499.4 2301.76   511.9 2302.53   519.4 2303.51
   529.4 2307.48   539.3  2309.5   619.2 2309.04   629.2 2309.19   639.2 2310.36
   689.2 2321.57   709.1 2323.73   759.1 2333.01     799 2341.47     819 2344.02
#Mann= 3 , 0 , 0
       0     .06       0   496.9    .045       0   511.9     .06       0
Bank Sta=496.9,511.9
XS Rating Curve= 0 ,0
Exp/Cntr=0.3,0.1

Type RM Length L Ch R = 1 ,12239   ,444.7,444.4,444.2
XS GIS Cut Line= 3
     1899102.963       257697.21     1898896.819      257343.381
      1898620.25      256873.707
#Sta/Elev= 30
       0 2387.77    49.9 2376.66    69.9 2374.15    89.9 2370.08   119.8 2362.11
   159.8  2353.3   169.8  2352.6   299.6 2321.07   329.6 2314.74   359.6  2309.2
   399.5  2307.9   426.3 2301.92   429.3 2301.49   441.3 2303.53     459 2308.36
     469 2309.12   587.9 2310.27   597.8 2310.66   617.6 2313.37   627.5 2314.92
   647.3 2319.71   657.2 2320.47   726.6 2338.27   766.3 2344.32   786.1 2351.16
   815.8 2357.99   845.5 2363.29   885.2 2368.78     905 2367.95   954.6 2361.18
#Mann= 3 , 0 , 0
       0     .06       0   426.3    .045       0   441.3     .06       0
Bank Sta=426.3,441.3
XS Rating Curve= 0 ,0
Exp/Cntr=0.3,0.1

Type RM Length L Ch R = 1 ,11794.4 ,401.2,400,398.4
XS GIS Cut Line= 3
     1899473.266      257437.988     1899261.281      257087.627
     1899049.297      256737.266
#Sta/Elev= 30
       0 2348.61      30 2345.03    69.9 2337.03    79.9 2337.55   129.8 2325.12
   179.8 2316.16   269.7  2310.5   279.7 2309.39   299.6 2304.55   319.6 2302.87
   349.6 2306.91   379.5 2307.02     402 2300.66   409.5 2299.71     417 2300.32
   429.5  2301.1   449.4 2305.95   469.4 2308.55   479.4  2312.4   509.4 2326.79
   519.4 2330.28   539.3 2335.02   549.3  2335.2   639.2 2360.04   659.2 2361.68
   689.2 2369.11   759.1 2383.79   769.1 2383.23     799 2387.94     819  2386.6
#Mann= 3 , 0 , 0
       0     .06       0     402    .045       0     417     .06       0
#XS Ineff= 2 , 0
           359.6  2307.3
Permanent Ineff=
       F       F
Bank Sta=402,417
XS Rating Curve= 0 ,0
Exp/Cntr=0.3,0.1

Type RM Length L Ch R = 1 ,11394.4 ,397,400.9,405.2
XS GIS Cut Line= 3
     1899822.168      257200.672     1899591.592      256862.169
     1899355.326      256527.717
#Sta/Elev= 30
       0 2346.74      10 2346.43    89.9 2339.06   119.9 2335.46   129.9 2333.23
   149.8  2330.8   189.8 2324.21   249.7 2312.65   269.7 2310.22   289.7 2305.92
   309.7  2304.2   379.6 2302.57   402.1 2297.47   409.6 2297.17   417.1 2298.91
   429.6 2302.54   439.5 2304.33   459.5 2305.91   489.5  2313.6   499.5 2314.07
   559.4 2332.11   599.3 2344.95   609.3 2347.76   619.3 2348.58   629.3 2351.27
   689.2 2375.07   719.2 2390.51   729.2 2392.19   769.1 2406.28   819.1 2415.73
#Mann= 3 , 0 , 0
       0     .06       0   402.1    .045       0   417.1     .06       0
Bank Sta=402.1,417.1
XS Rating Curve= 0 ,0
Exp/Cntr=0.3,0.1

Type RM Length L Ch R = 1 ,10993.5 ,596.8,612.7,628.7
XS GIS Cut Line= 3
     1900126.194      257075.804     1899875.466      256521.523
     1900312.524      255373.191
#Sta/Elev= 30
       0 2374.14   139.6 2346.82   249.3 2305.92   269.3 2301.38   408.9 2301.86
   439.2 2295.45   448.8 2294.39   454.2 2294.42   518.6 2301.66   608.4 2345.33
   688.3 2360.51   708.2  2367.4   718.2 2366.32   798.2 2399.12   868.1 2412.63
     958 2417.73  1077.8 2410.84  1357.6  2339.6  1427.5 2354.55  1457.4 2364.61
  1517.4 2374.86  1527.4 2378.04  1567.3 2404.91  1607.3 2426.13  1657.2 2429.79
  1717.2 2412.71  1727.2 2412.88  1757.1  2391.9  1807.1 2347.43    1837 2335.38
#Mann= 3 , 0 , 0
       0      .1       0   439.2    .045       0   454.2      .1       0
#XS Ineff= 2 , 0
          358.41 2302.64
Permanent Ineff=
       F       F
Bank Sta=439.2,454.2
XS Rating Curve= 0 ,0
Exp/Cntr=0.3,0.1

Type RM Length L Ch R = 1 ,10380.8 ,191,199.7,208.4
XS GIS Cut Line= 3
     1900377.257      257036.594      1900614.52      256222.281
     1901095.962      255500.117
#Sta/Elev= 30
       0 2365.45    79.8 2355.58   139.7 2359.44   199.6 2347.28   259.4  2329.7
   329.3  2316.2   399.1 2298.46     449  2294.4   459.1  2294.4   474.1 2294.82
   498.9 2298.94   728.4 2303.02   778.3 2316.04   818.2 2314.42     908 2325.26
   957.9 2334.57   987.8 2344.84  1077.6 2360.48  1167.4 2361.05  1257.2 2338.74
    1337 2325.01  1376.9 2323.77  1436.8  2340.6  1486.6 2362.04  1506.6 2367.23
  1546.5  2387.4  1566.5 2394.09  1606.4 2398.85  1646.3 2396.17  1716.1 2409.19
#Mann= 3 , 0 , 0
       0      .1       0   459.1    .045       0   474.1      .1       0
Bank Sta=459.1,474.1
XS Rating Curve= 0 ,0
Exp/Cntr=0.3,0.1

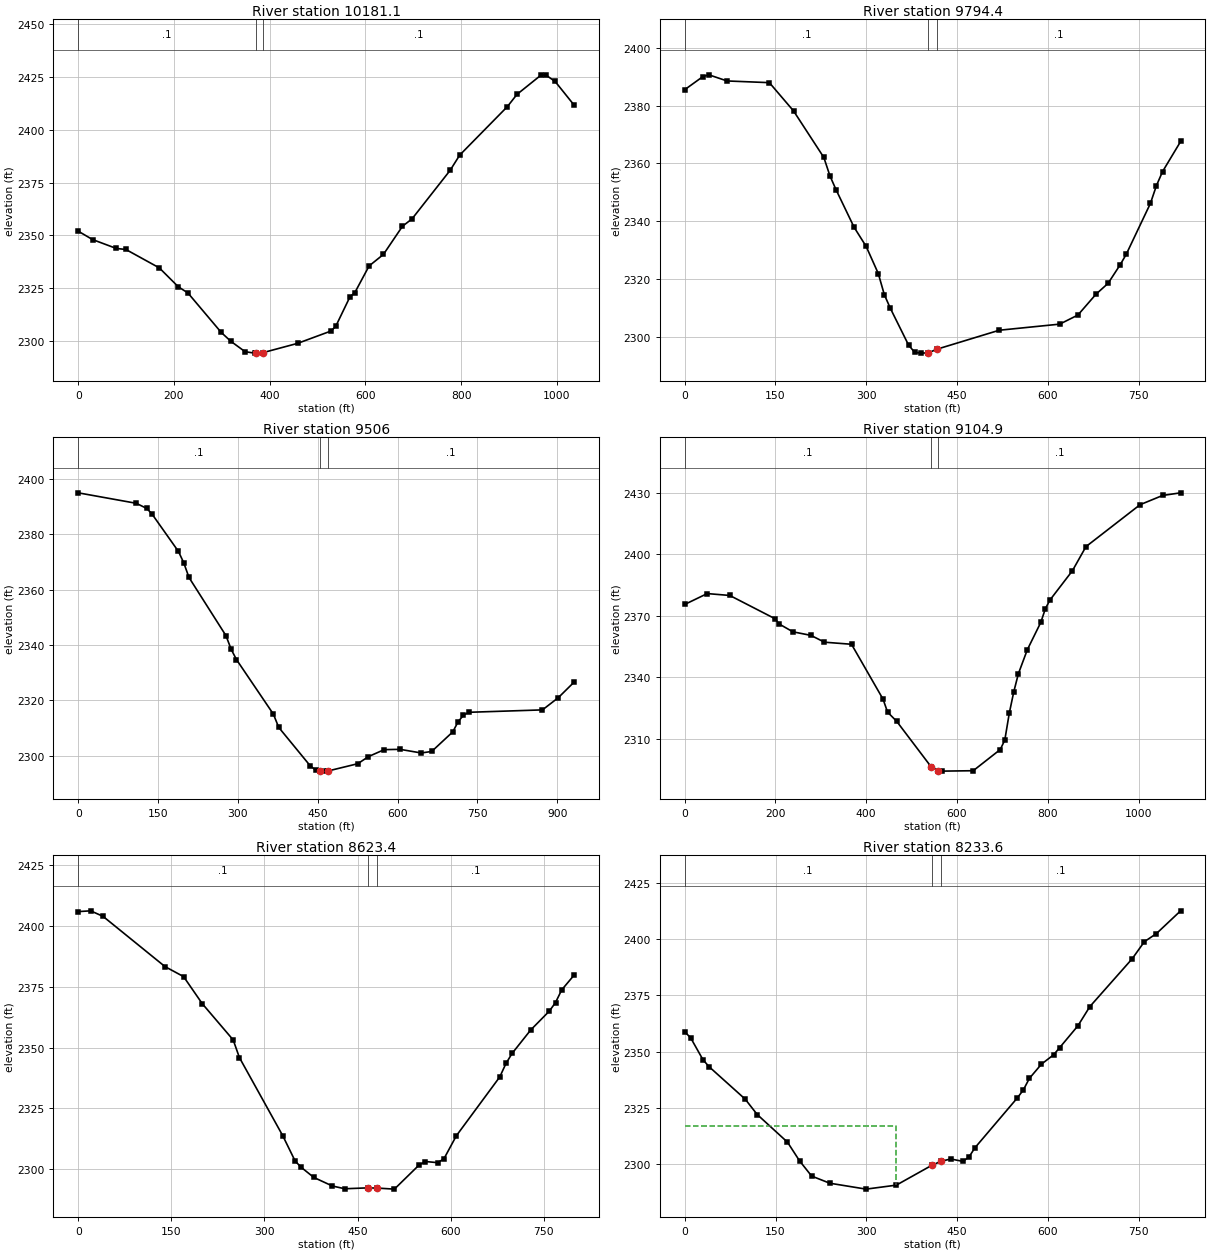
Type RM Length L Ch R = 1 ,10181.1 ,376.6,386.6,397.3
XS GIS Cut Line= 2
      1900441.29      256984.263     1901083.435      256170.987
#Sta/Elev= 30
       0 2352.02    29.9 2348.06    79.7 2343.85    99.6 2343.37   169.4 2334.68
   209.2 2325.73   229.2 2322.83   298.9 2304.16   318.8 2300.01   348.7 2295.07
   368.7  2294.4   371.4 2294.41   386.4 2294.65   458.3 2299.01   528.1 2304.84
     538 2307.03   567.9 2321.05   577.9 2322.97   607.8  2335.6   637.7 2341.03
   677.5 2354.34   697.5 2357.84   777.2 2380.79   797.1 2387.96   896.7 2410.87
   916.7 2416.63   966.5 2425.67   976.4 2425.88   996.4 2422.76  1036.2 2411.54
#Mann= 3 , 0 , 0
       0      .1       0   371.4    .045       0   386.4      .1       0
Bank Sta=371.4,386.4
XS Rating Curve= 0 ,0
Exp/Cntr=0.3,0.1

Type RM Length L Ch R = 1 ,9794.4  ,285.7,288.3,290.2
XS GIS Cut Line= 3
     1900570.328      257141.736     1900937.724       256960.23
     1901310.743      256791.395
#Sta/Elev= 30
       0 2385.49      30 2390.02      40 2390.64      70 2388.52   139.9 2387.93
   179.9 2378.13   229.9 2362.04   239.9 2355.71   249.9 2350.95   279.8 2337.92
   299.8 2331.26   319.8  2321.9   329.8 2314.57   339.8 2309.83   369.8 2297.16
   379.8 2294.65   389.8 2294.36   402.3 2294.46   417.3 2295.76   519.6 2302.28
   619.5 2304.39   649.5 2307.53   679.4 2314.74   699.4 2318.51   719.4 2324.94
   729.4 2328.56   769.3 2346.16   779.3 2352.34   789.3 2357.15   819.2 2367.58
#Mann= 3 , 0 , 0
       0      .1       0   402.3    .045       0   417.3      .1       0
Bank Sta=402.3,417.3
XS Rating Curve= 0 ,0
Exp/Cntr=0.3,0.1

Type RM Length L Ch R = 1 ,9506    ,399.8,400.8,401.8
XS GIS Cut Line= 2
     1900604.271      257385.196     1901481.109      257070.642
#Sta/Elev= 30
       0 2394.92     109 2391.14   128.8 2389.28   138.7 2387.24   188.3 2373.74
   198.2 2369.67   208.1 2364.34   277.5 2343.34   287.4 2338.37   297.3 2334.68
   366.7 2314.96   376.6 2310.21     436 2296.28     446  2294.8   453.9 2294.49
   465.8  2294.4   468.9 2294.44   525.2 2297.08   545.1 2299.64   574.8 2302.16
   604.5 2302.27   644.2 2300.96     664  2301.5   703.6 2308.58   713.5 2312.19
   723.4 2314.54   733.4 2315.65   872.1 2316.52   901.8 2320.93   931.6 2326.57
#Mann= 3 , 0 , 0
       0      .1       0   453.9    .045       0   468.9      .1       0
Bank Sta=453.9,468.9
XS Rating Curve= 0 ,0
Exp/Cntr=0.3,0.1

Type RM Length L Ch R = 1 ,9104.9  ,483,481.6,480.2
XS GIS Cut Line= 2
     1900607.531      257750.273     1901650.609      257424.311
#Sta/Elev= 30
       0 2375.51    49.7 2380.81    99.4 2379.89   198.7 2368.61   208.6 2365.95
   238.4  2362.2   278.2 2360.46     308 2357.14   367.6 2356.13   437.1  2329.4
   447.1 2323.08   466.9 2318.69     543 2296.49     558 2294.45   566.3 2294.37
   635.8 2294.57   695.4 2304.89   705.4 2309.52   715.3 2322.63   725.2 2333.03
   735.2 2341.71     755 2353.47   784.8 2366.84   794.8 2373.46   804.7 2377.62
   854.4 2391.94   884.2 2403.66  1003.4 2424.07  1053.1 2428.58  1092.8 2429.86
#Mann= 3 , 0 , 0
       0      .1       0     543    .045       0     558      .1       0
Bank Sta=543,558
XS Rating Curve= 0 ,0
Exp/Cntr=0.3,0.1

Type RM Length L Ch R = 1 ,8623.4  ,391.8,389.4,386.6
XS GIS Cut Line= 2
     1900896.007      258169.134     1901637.571      257872.509
#Sta/Elev= 30
       0 2405.97      20 2406.29    39.9 2404.03   139.8 2383.35   169.7 2379.24
   199.7 2368.13   249.6 2353.19   259.6 2345.94   329.5 2313.76   349.4 2303.37
   359.4 2300.75   379.4 2296.65   409.3 2293.13   429.3 2291.99   466.5 2292.36
   481.5 2292.27   509.2 2291.84   549.1 2301.79   559.1  2303.2     579 2302.72
     589 2304.32     609 2313.79   678.9 2337.98   688.9 2343.52   698.8 2347.67
   728.8 2357.31   758.8 2365.07   768.7 2368.58   778.7  2373.8   798.7 2379.87
#Mann= 3 , 0 , 0
       0      .1       0   466.5    .045       0   481.5      .1       0
Bank Sta=466.5,481.5
XS Rating Curve= 0 ,0
Exp/Cntr=0.3,0.1

Type RM Length L Ch R = 1 ,8233.6  ,408.4,393.9,379.7
XS GIS Cut Line= 3
     1901206.102      258476.419     1901561.576      258273.176
     1901912.222      258061.387
#Sta/Elev= 30
       0 2358.86      10 2356.07      30 2346.47      40 2343.33    99.9 2328.83
   119.8 2321.97   169.8 2309.65   189.8 2301.31   209.7 2294.55   239.7 2291.37
   299.6 2288.74   349.6 2290.52   408.1 2299.34   423.1 2301.12   439.4 2302.17
   459.4  2301.1   469.4 2302.99   479.4 2307.16   549.4 2329.36   559.3 2332.89
   569.3 2338.06   589.3 2344.42   609.3 2348.56   619.3 2351.75   649.3 2361.42
   669.2 2370.04   739.2 2391.37   759.2 2398.94   779.2 2402.57   819.1 2412.69
#Mann= 3 , 0 , 0
       0      .1       0   408.1    .045       0   423.1      .1       0
#XS Ineff= 2 , 0
          348.33 2316.93
Permanent Ineff=
       F       F
Bank Sta=408.1,423.1
XS Rating Curve= 0 ,0
Exp/Cntr=0.3,0.1

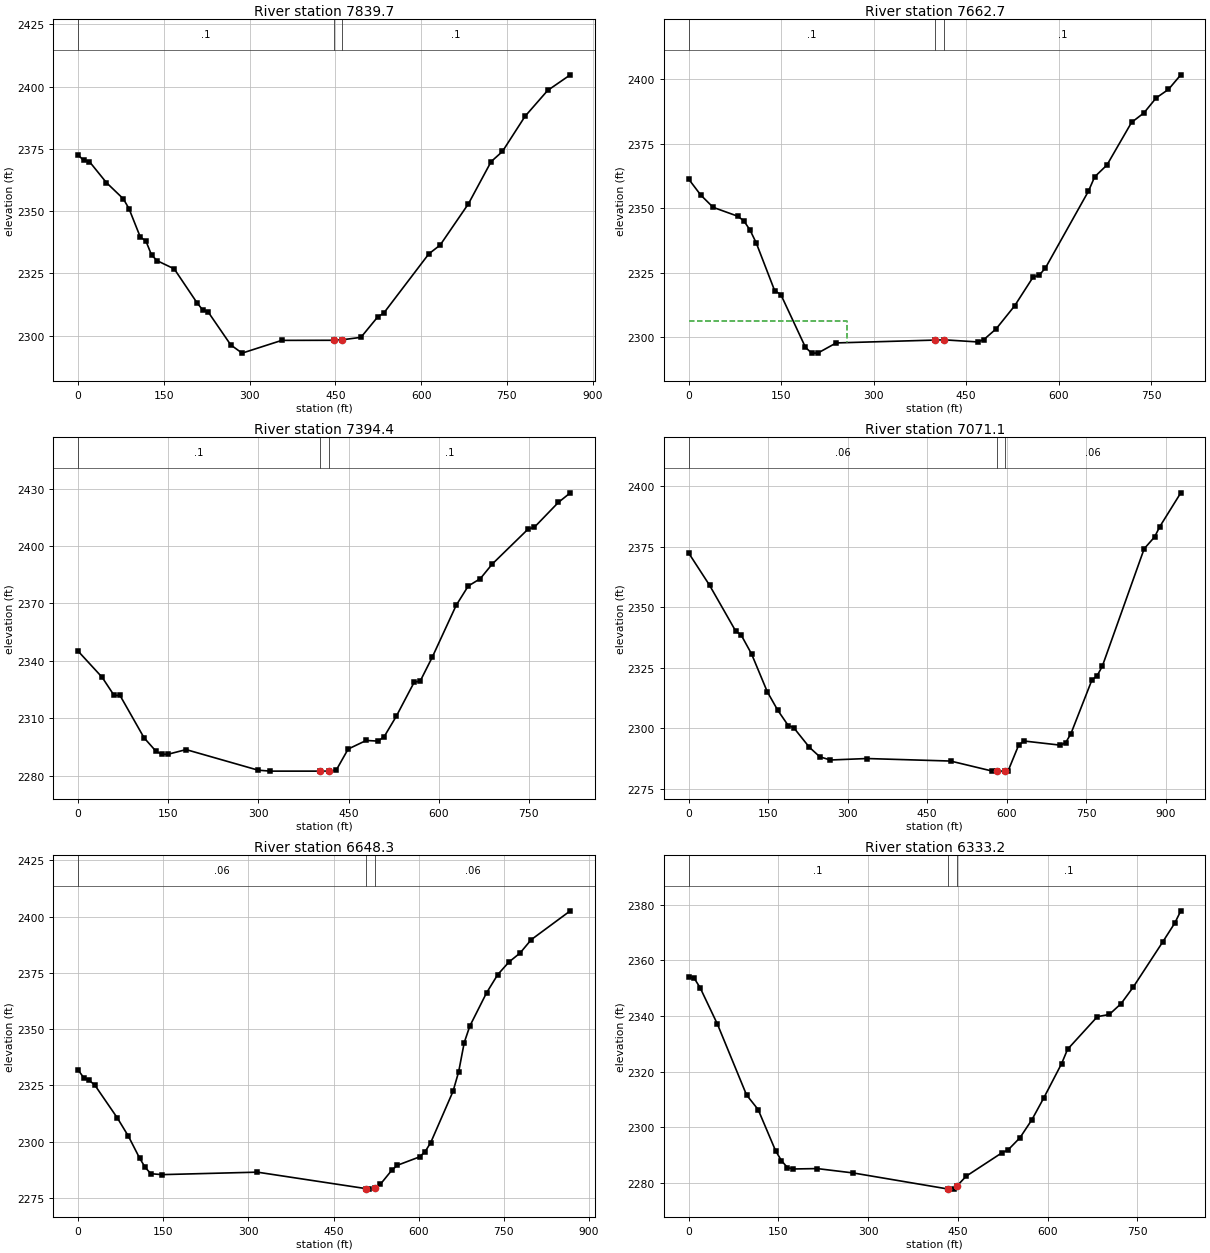
Type RM Length L Ch R = 1 ,7839.7  ,176.3,176.9,177.5
XS GIS Cut Line= 2
     1901655.673      258948.511     1902000.268        258159.7
#Sta/Elev= 30
       0  2372.6     9.9 2370.38    19.8 2369.94    49.5  2361.5    79.2 2354.95
      89 2351.07   108.8 2339.64   118.7    2338   128.6 2332.36   138.5 2330.08
   168.2 2326.82   207.8 2313.28   217.7 2310.39   227.6 2309.48   267.1 2296.26
   286.9 2292.97   356.2 2298.09   446.9 2298.13   461.9 2298.33   494.7 2299.31
   524.4 2307.62   534.3 2308.96   613.4 2332.84   633.2 2336.37   682.7 2352.98
   722.3 2369.89   742.1 2373.98   781.6 2388.09   821.2  2398.5   860.8 2404.77
#Mann= 3 , 0 , 0
       0      .1       0   446.9    .045       0   461.9      .1       0
Bank Sta=446.9,461.9
XS Rating Curve= 0 ,0
Exp/Cntr=0.3,0.1

Type RM Length L Ch R = 1 ,7662.7  ,270.4,268.3,266.1
XS GIS Cut Line= 2
     1901822.864      258977.908     1902162.559      258256.056
#Sta/Elev= 30
       0 2361.31    19.9 2355.04    39.9 2350.31    79.8 2346.87    89.8 2345.04
    99.7  2341.5   109.7 2336.56   139.6 2318.06   149.6 2316.56   189.5 2296.14
   199.4  2293.9   209.4 2293.89   239.3 2297.84   399.7 2298.94   414.7 2299.03
   468.7 2298.22   478.7 2299.15   498.6  2303.3   528.5 2312.19   558.4  2323.3
   568.4 2324.06   578.4 2326.84   648.2  2356.6   658.2 2362.11   678.1 2366.68
     718 2383.18     738 2386.84   757.9 2392.66   777.8 2395.95   797.8 2401.59
#Mann= 3 , 0 , 0
       0      .1       0   399.7    .045       0   414.7      .1       0
#XS Ineff= 2 , 0
          256.32 2306.41
Permanent Ineff=
       F       F
Bank Sta=399.7,414.7
XS Rating Curve= 0 ,0
Exp/Cntr=0.3,0.1

Type RM Length L Ch R = 1 ,7394.4  ,330.9,323.3,315.8
XS GIS Cut Line= 3
     1902105.467      259096.864     1902244.173      258711.571
     1902382.879      258326.278
#Sta/Elev= 30
       0  2345.1      40 2331.43    59.9 2321.95    69.9 2321.86   109.9 2299.71
   129.8 2292.66   139.8 2291.08   149.8 2291.14   179.8 2293.56   299.6  2282.8
   319.6  2282.3     402  2282.3     417  2282.3   429.5 2282.77   449.4 2293.85
   479.4 2298.34   499.4    2298   509.4 2300.37   529.4 2310.94   559.3 2328.83
   569.3  2329.4   589.3 2341.87   629.2 2369.07   649.2 2379.12   669.2 2382.96
   689.2 2390.64   749.1    2409   759.1 2409.83     799 2422.82     819 2427.87
#Mann= 3 , 0 , 0
       0      .1       0     402    .045       0     417      .1       0
Bank Sta=402,417
XS Rating Curve= 0 ,0
Exp/Cntr=0.3,0.1

Type RM Length L Ch R = 1 ,7071.1  ,407,422.8,438.6
XS GIS Cut Line= 3
      1902452.65      259319.236     1902557.172      259116.726
     1902565.337      258416.105
#Sta/Elev= 30
       0  2372.4    39.6 2359.04    89.2 2340.01    99.1 2338.55   118.9 2330.67
   148.6 2315.04   168.4 2307.39   188.3 2301.05   198.2 2300.29   227.9 2292.16
   247.6 2288.23   267.4 2286.89   336.4  2287.5   494.3 2286.46   573.3  2282.3
   581.3  2282.3   596.3 2282.34   602.9 2282.42   622.6 2292.95   632.5 2294.74
   701.6 2293.01   711.4 2294.05   721.3 2297.74   760.8 2319.84   770.7 2321.66
   780.5 2325.56   859.5 2374.07   879.2 2378.96   889.1 2383.25   928.6 2397.15
#Mann= 3 , 0 , 0
       0     .06       0   581.3    .045       0   596.3     .06       0
Bank Sta=581.3,596.3
XS Rating Curve= 0 ,0
Exp/Cntr=0.3,0.1

Type RM Length L Ch R = 1 ,6648.3  ,304.6,315.1,325.7
XS GIS Cut Line= 3
     1902704.155      259262.076     1902944.228      258853.789
     1903179.402      258538.591
#Sta/Elev= 30
       0 2331.95     9.9 2328.46    19.7 2327.27    29.6 2325.14    69.1 2310.61
    88.8 2302.41   108.5 2292.68   118.4 2288.55   128.3 2285.78     148 2285.38
   315.8 2286.48   507.7 2279.14     513 2278.94   522.7 2279.36   532.6 2281.15
   552.3 2287.26   562.1 2289.51   601.4 2293.26   611.3 2295.63   621.1 2299.62
   660.4  2322.4   670.3 2331.08   680.1 2344.03   689.9 2351.35   719.4 2366.13
   739.1 2374.24   758.8 2379.81   778.4 2383.82   798.1 2389.76   866.9 2402.57
#Mann= 3 , 0 , 0
       0     .06       0   507.7    .045       0   522.7     .06       0
Bank Sta=507.7,522.7
XS Rating Curve= 0 ,0
Exp/Cntr=0.3,0.1

Type RM Length L Ch R = 1 ,6333.2  ,257.2,259.6,262.1
XS GIS Cut Line= 3
     1902808.677        259342.1      1902872.37      259211.448
     1903478.268      258909.316
#Sta/Elev= 30
       0 2354.24     9.7 2353.55    19.4 2350.21    48.4 2337.07    96.9 2311.71
   116.3 2306.44   145.4 2291.67   155.3 2288.07   165.3  2285.6   175.2  2285.1
     215 2285.24   274.8 2283.68   433.3 2277.91     444 2277.86   448.3 2278.97
     464 2282.53   523.7 2290.93   533.7 2291.92   553.6 2296.29   573.5 2302.74
   593.4 2310.59   623.3 2322.96   633.2 2328.08     683 2339.82   702.9  2340.6
   722.8 2344.53   742.8  2350.4   792.5 2366.76   812.4 2373.46   822.4 2377.84
#Mann= 3 , 0 , 0
       0      .1       0   433.3    .045       0   448.3      .1       0
Bank Sta=433.3,448.3
XS Rating Curve= 0 ,0
Exp/Cntr=0.3,0.1

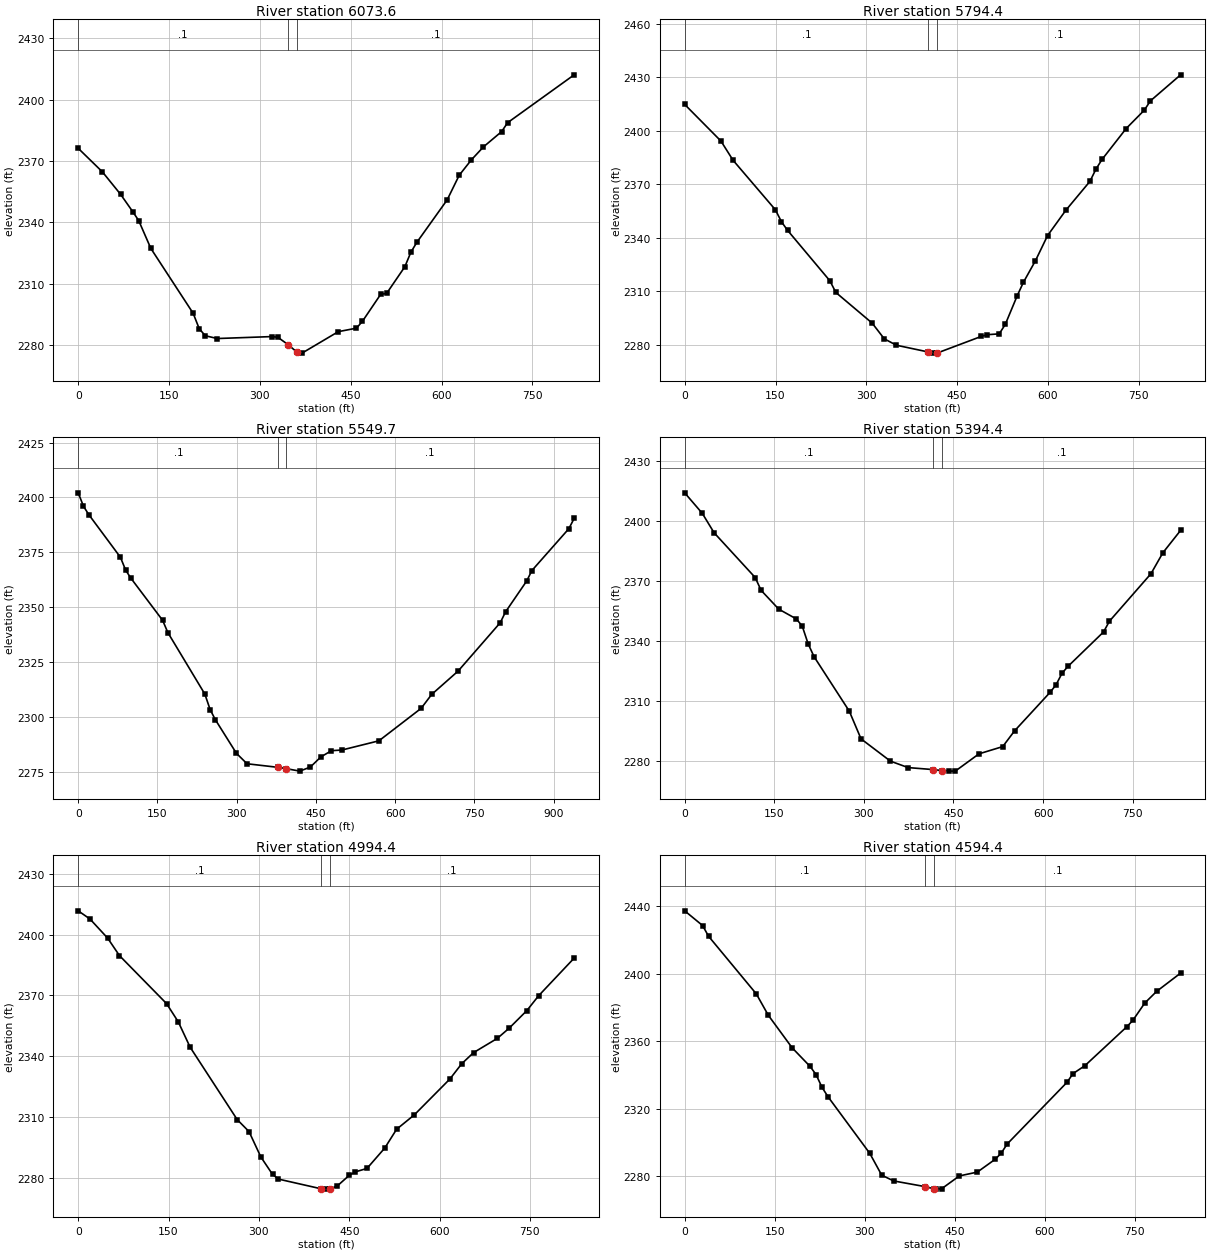
Type RM Length L Ch R = 1 ,6073.6  ,280,279.1,278.2
XS GIS Cut Line= 3
     1902891.517      259445.504     1903275.939      259304.326
     1903661.745      259167.068
#Sta/Elev= 30
       0 2376.19      40 2364.66    69.9 2353.74    89.9 2345.31    99.9 2340.89
   119.9 2327.31   189.8 2295.61   199.8 2288.11   209.8 2284.64   229.7 2283.28
   319.6 2284.23   329.6 2283.91   346.7 2280.27   361.7 2276.51   369.6 2276.15
   429.5 2286.64   459.5 2288.34   469.4 2291.71   499.4 2304.83   509.4 2305.35
   539.4 2318.34   549.4 2325.46   559.3  2330.3   609.3 2351.01   629.2 2363.04
   649.2 2370.53   669.2 2376.88   699.2 2384.34   709.2 2388.72     819 2412.08
#Mann= 3 , 0 , 0
       0      .1       0   346.7    .045       0   361.7      .1       0
Bank Sta=346.7,361.7
XS Rating Curve= 0 ,0
Exp/Cntr=0.3,0.1

Type RM Length L Ch R = 1 ,5794.4  ,235.7,244.7,253.7
XS GIS Cut Line= 3
     1902939.816       259741.12     1903317.988      259584.032
     1903696.159      259426.944
#Sta/Elev= 30
       0 2414.75    59.9 2394.21    79.9 2383.45   149.8  2355.7   159.8    2349
   169.8 2344.22   239.7 2315.94   249.7 2309.35   309.6 2292.19   329.6 2283.39
   349.6  2279.8     402 2276.03   409.5 2275.37     417 2275.43   489.4 2284.69
   499.4  2285.7   519.4 2286.16   529.4 2291.43   549.3 2307.65   559.3    2315
   579.3 2327.18   599.3 2341.25   629.2 2355.33   669.2 2371.61   679.2 2378.49
   689.2  2383.9   729.1 2401.24   759.1 2411.54   769.1 2416.73     819 2431.33
#Mann= 3 , 0 , 0
       0      .1       0     402    .045       0     417      .1       0
Bank Sta=402,417
XS Rating Curve= 0 ,0
Exp/Cntr=0.3,0.1

Type RM Length L Ch R = 1 ,5549.7  ,150.5,155.3,160.7
XS GIS Cut Line= 2
     1902998.122      259815.714     1903937.183      259817.347
#Sta/Elev= 30
       0 2402.13      10 2395.99      20  2392.2    79.9 2372.74    89.9 2366.83
    99.9 2363.14   159.8 2343.98   169.8 2338.35   239.8 2310.31   249.8 2303.24
   259.7 2298.62   299.7 2283.26   319.7 2278.53     379 2276.88     394  2276.3
   419.6 2275.17   439.6 2277.04   459.5 2281.66   479.5 2284.49   499.5 2284.81
   569.4    2289   649.4 2303.82   669.3 2310.16   719.3  2320.8   799.2  2342.9
   809.2 2347.82   849.2  2361.9   859.1 2366.68   929.1 2385.78   939.1 2390.48
#Mann= 3 , 0 , 0
       0      .1       0     379    .045       0     394      .1       0
Bank Sta=379,394
XS Rating Curve= 0 ,0
Exp/Cntr=0.3,0.1

Type RM Length L Ch R = 1 ,5394.4  ,386.4,400,411.6
XS GIS Cut Line= 3
     1902965.245      259880.056     1903378.789      259969.762
     1903774.108      260066.945
#Sta/Elev= 30
       0 2414.32    29.5 2404.05    49.2 2394.36   118.1 2371.94   127.9 2365.56
   157.5 2356.14     187 2351.24   196.8 2347.65   206.7 2338.78   216.5 2332.41
   275.6  2305.1   295.2 2291.27   344.4 2280.13     374  2276.9   415.7 2275.91
   430.7 2275.41     443 2275.13     453 2275.14   492.7 2283.78   532.4  2287.4
   552.2 2295.26   611.8 2314.57   621.7 2318.32   631.7  2324.1   641.6 2327.51
   701.2 2344.75   711.1 2350.14   780.6 2373.88   800.5 2384.34   830.2 2395.55
#Mann= 3 , 0 , 0
       0      .1       0   415.7    .045       0   430.7      .1       0
Bank Sta=415.7,430.7
XS Rating Curve= 0 ,0
Exp/Cntr=0.3,0.1

Type RM Length L Ch R = 1 ,4994.4  ,405.1,399.9,400.4
XS GIS Cut Line= 3
     1902892.194      260008.353     1903174.514       260306.68
     1903476.852      260587.602
#Sta/Elev= 30
       0 2411.71    19.6 2407.66    48.9 2398.25    68.5 2389.64   146.7 2365.99
   166.2 2356.98   185.8 2344.52     264 2308.83   283.6 2302.94   303.2 2290.45
   322.7 2281.82   332.5 2279.53   403.2 2274.76   410.7 2274.59   418.2 2274.71
   430.4 2276.22     450 2281.39   459.9 2283.07   479.5  2284.8     509 2294.85
   528.6 2304.08   558.1  2311.2   617.1 2328.85   636.7 2336.36   656.4 2341.85
   695.7 2348.84   715.4 2353.86   744.8 2362.54   764.5  2369.9   823.4 2388.41
#Mann= 3 , 0 , 0
       0      .1       0   403.2    .045       0   418.2      .1       0
Bank Sta=403.2,418.2
XS Rating Curve= 0 ,0
Exp/Cntr=0.3,0.1

Type RM Length L Ch R = 1 ,4594.4  ,325.1,322.8,316.3
XS GIS Cut Line= 3
     1902596.498      260378.385     1902936.601      260603.648
     1903236.159      260895.681
#Sta/Elev= 30
       0 2437.43    29.8 2428.71    39.8 2422.33   119.4  2388.1   139.3 2375.46
   179.1 2356.11   208.9  2345.1   218.9 2340.23   228.8 2332.67   238.8 2327.08
   308.4 2293.48   328.3 2280.53   348.2 2277.11   400.4 2273.75   415.4 2272.46
   417.9 2272.25   427.9 2272.42   457.7 2280.09   487.6 2282.36   517.5 2290.01
   527.5 2293.66   537.4 2299.06     637 2335.64     647 2340.81   666.9 2345.54
   736.6  2368.6   746.6 2372.36   766.5 2382.66   786.4 2389.64   826.3 2400.47
#Mann= 3 , 0 , 0
       0      .1       0   400.4    .045       0   415.4      .1       0
Bank Sta=400.4,415.4
XS Rating Curve= 0 ,0
Exp/Cntr=0.3,0.1