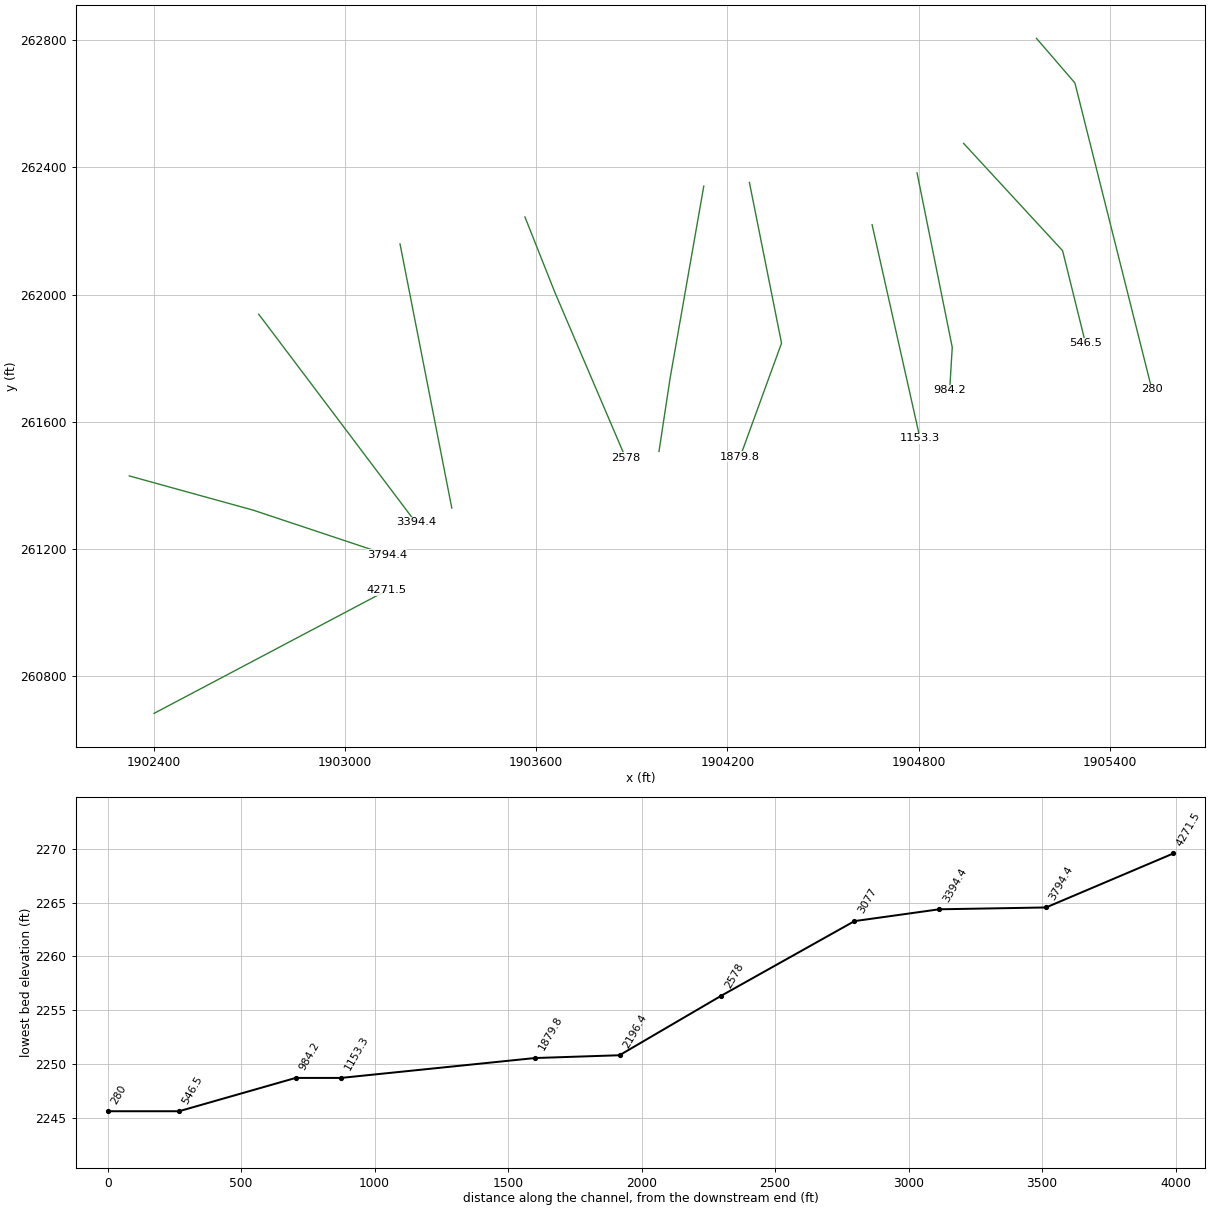
HEC-RAS study SkCrk.prj: SkCrk

--- SkCrk.g01 (geometry) --- (continued)

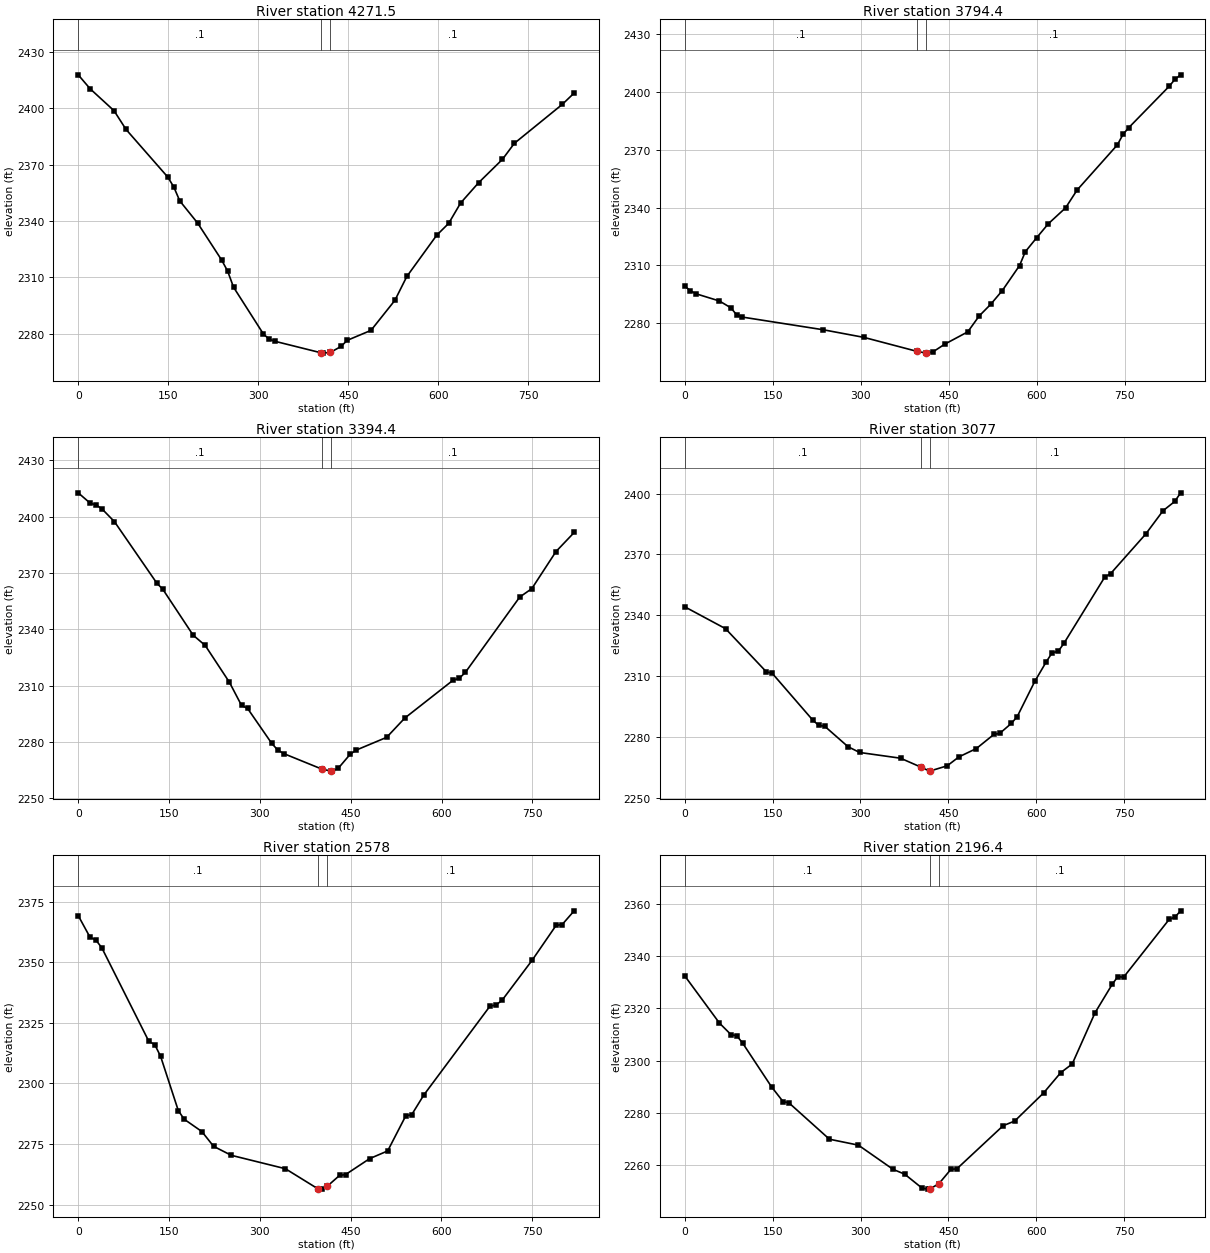
Type RM Length L Ch R = 1 ,4271.5  ,494.6,477.2,458.6
XS GIS Cut Line= 2
     1902401.142      260683.226     1903131.418      261069.798
#Sta/Elev= 30
       0 2417.91    19.9 2410.46    59.7 2398.78    79.6 2388.84   149.3 2363.39
   159.3 2358.11   169.2 2350.73   199.1 2338.85   238.9 2319.24   248.9 2313.34
   258.8 2304.73   308.6 2279.76   318.6 2276.93   328.5 2275.84   405.2 2269.72
   408.2 2269.59   420.2 2269.99     438 2273.17     448 2276.38   487.8 2281.72
   527.6 2297.71   547.5 2310.43   597.3 2332.43   617.2 2338.73   637.1 2349.58
     667 2360.38   706.8 2372.86   726.7 2381.41   806.4 2402.12   826.3 2408.21
#Mann= 3 , 0 , 0
       0      .1       0   405.2    .045       0   420.2      .1       0
Bank Sta=405.2,420.2
XS Rating Curve= 0 ,0
Exp/Cntr=0.3,0.1

Type RM Length L Ch R = 1 ,3794.4  ,414.9,399.9,386.2
XS GIS Cut Line= 3
     1902323.364      261429.883     1902712.647      261322.081
     1903130.985      261182.409
#Sta/Elev= 30
       0 2299.31     9.8 2296.86    19.7 2295.28    59.1 2291.59    78.8 2288.03
    88.7 2284.31    98.5 2283.23   236.4 2276.65   305.4 2272.72   396.4 2265.43
   411.4 2264.62   413.7 2264.56   423.5  2265.3   443.1  2269.2   482.3 2275.58
   501.9 2283.86   521.5 2289.88   541.2 2296.98   570.6 2309.96   580.4 2317.12
     600 2324.46   619.6 2331.61     649 2339.85   668.6 2349.07   737.2 2372.47
     747 2377.99   756.8 2381.45   825.4  2402.8   835.2  2406.4     845 2408.78
#Mann= 3 , 0 , 0
       0      .1       0   396.4    .045       0   411.4      .1       0
Bank Sta=396.4,411.4
XS Rating Curve= 0 ,0
Exp/Cntr=0.3,0.1

Type RM Length L Ch R = 1 ,3394.4  ,327.5,317.5,308.2
XS GIS Cut Line= 3
     1902729.409      261938.497      1902975.64      261611.296
     1903221.871      261284.094
#Sta/Elev= 30
       0 2412.69      20 2407.11      30  2406.2      40 2403.88    59.9  2397.3
   129.8 2364.57   139.8 2361.25   189.8 2336.84   209.7 2331.37   249.7 2311.74
   269.7 2299.41   279.7  2297.8   319.6 2279.16   329.6 2275.61   339.6 2273.71
     402 2265.52     417 2264.45   419.5 2264.39   429.5 2265.93   449.4 2273.47
   459.4 2275.64   509.4  2282.4   539.3 2292.66   619.2 2312.88   629.2 2313.84
   639.2 2316.95   729.1 2357.14   749.1 2361.64     789  2381.4     819 2391.55
#Mann= 3 , 0 , 0
       0      .1       0     402    .045       0     417      .1       0
Bank Sta=402,417
XS Rating Curve= 0 ,0
Exp/Cntr=0.3,0.1

Type RM Length L Ch R = 1 ,3077    ,494.4,498.7,502.4
XS GIS Cut Line= 2
     1903172.869      262159.283      1903335.36      261328.758
#Sta/Elev= 30
       0 2344.24    69.7 2333.45   139.4 2312.18   149.3 2311.49     219 2288.27
     229 2285.81     239 2285.39   278.8  2275.3   298.7 2272.47   368.4 2269.65
     403 2265.28     418 2263.29     448 2265.91   467.9 2270.29   497.8 2274.42
   527.7 2281.38   537.6 2281.87   557.5 2286.81   567.5 2290.16   597.4 2307.47
   617.3 2317.26   627.2 2321.64   637.2 2322.21   647.2 2326.24   716.8 2358.84
   726.8 2360.54   786.5 2379.96   816.4 2391.56   836.3  2396.1   846.3 2400.35
#Mann= 3 , 0 , 0
       0      .1       0     403    .045       0     418      .1       0
Bank Sta=403,418
XS Rating Curve= 0 ,0
Exp/Cntr=0.3,0.1

Type RM Length L Ch R = 1 ,2578    ,394.6,381.3,368
XS GIS Cut Line= 3
     1903564.825      262244.207     1903657.914      262009.034
     1903880.196      261487.754
#Sta/Elev= 30
       0 2369.22    19.5  2360.3    29.2 2359.12    38.9 2355.97   116.7 2317.34
   126.5 2315.99   136.2 2311.11   165.4 2288.76   175.1  2285.2   204.3 2280.12
   223.7 2274.02   252.9 2270.31   342.4 2264.77   396.5 2256.42   402.1 2256.35
   411.5 2257.52   431.9 2262.01   441.8 2262.35   481.6 2268.93   511.4 2272.11
   541.2 2286.54   551.2  2287.1   571.1 2295.17   680.4 2331.83   690.4 2332.34
   700.3 2334.22     750 2350.74   789.8  2365.2   799.7  2365.5   819.6 2371.19
#Mann= 3 , 0 , 0
       0      .1       0   396.5    .045       0   411.5      .1       0
Bank Sta=396.5,411.5
XS Rating Curve= 0 ,0
Exp/Cntr=0.3,0.1

Type RM Length L Ch R = 1 ,2196.4  ,308.7,316.7,324.7
XS GIS Cut Line= 3
     1904126.038      262341.265     1904020.474      261737.931
     1903985.432      261506.837
#Sta/Elev= 30
       0 2332.49    59.3 2314.39      79 2309.96    88.9 2309.53    98.8 2306.75
   148.2 2289.97   167.9 2284.31   177.8 2283.86     247 2269.92   296.4 2267.65
   355.6 2258.38   375.4 2256.54     405  2251.2   414.9 2250.81   418.7 2250.94
   433.7 2252.87   454.4 2258.42   464.3 2258.56   543.4  2275.1   563.1 2276.88
   612.5 2287.66   641.7 2295.42   661.2 2298.71   700.2 2318.35   729.4 2329.19
   739.1  2332.2   748.8 2331.92   826.8 2354.12   836.5 2354.95   846.2 2357.36
#Mann= 3 , 0 , 0
       0      .1       0   418.7    .045       0   433.7      .1       0
Bank Sta=418.7,433.7
XS Rating Curve= 0 ,0
Exp/Cntr=0.3,0.1

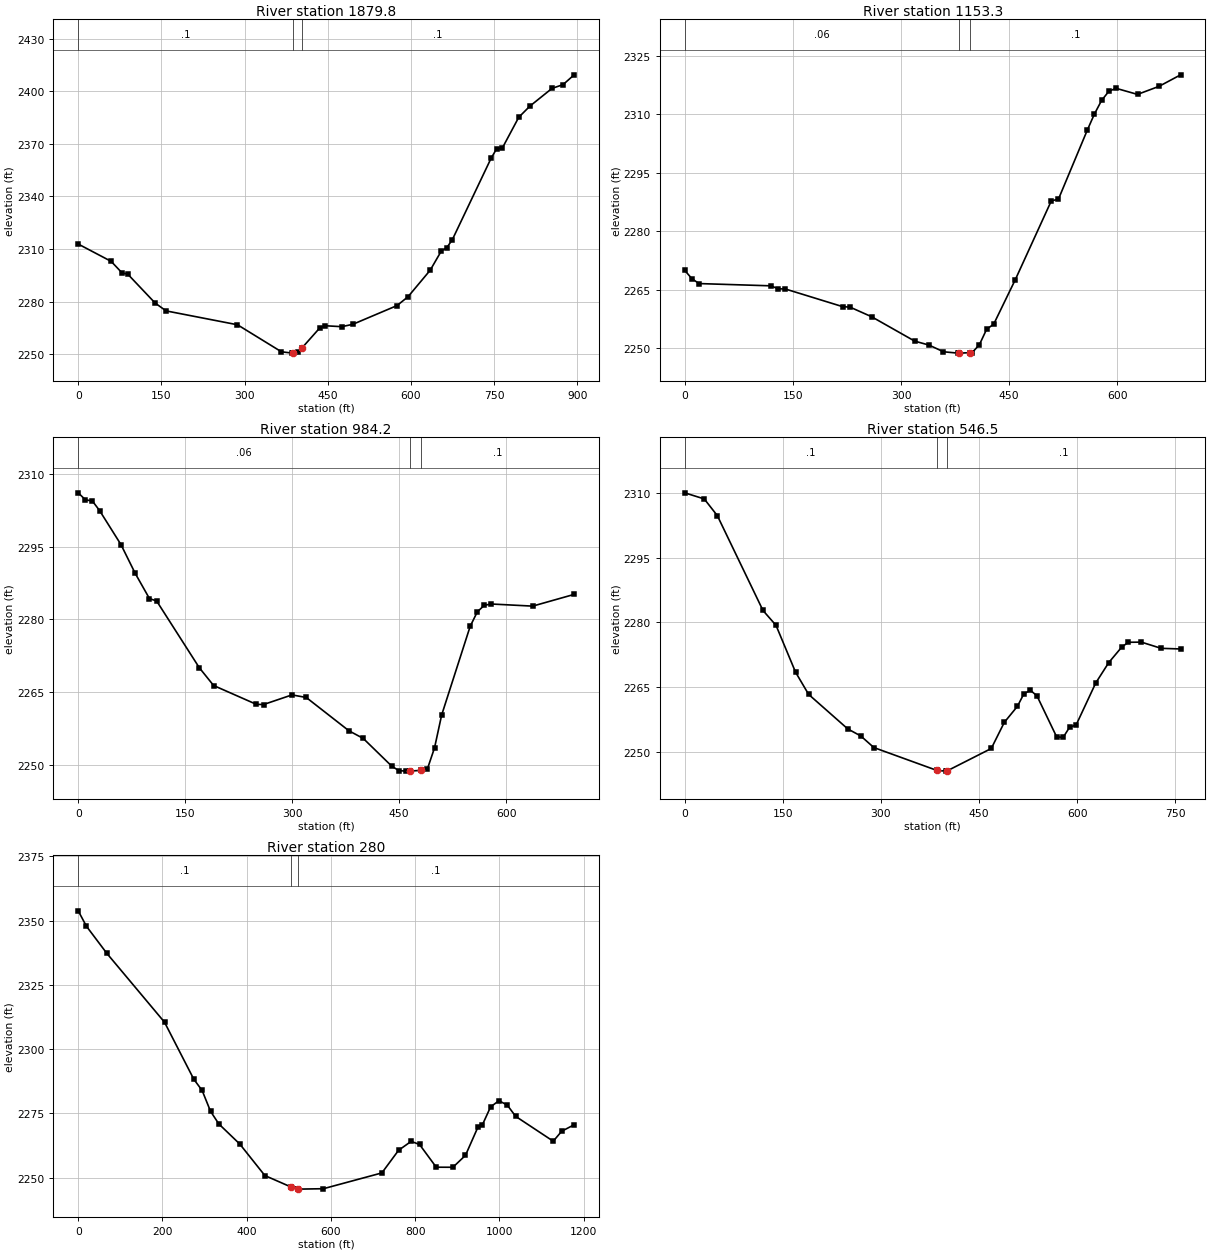
Type RM Length L Ch R = 1 ,1879.8  ,726.3,726.6,726.8
XS GIS Cut Line= 3
     1904269.175      262352.557     1904369.968      261847.352
     1904240.479      261490.698
#Sta/Elev= 30
       0 2312.79    59.4 2302.91    79.3 2296.25    89.2 2295.67   138.7 2279.14
   158.5 2274.65   287.3 2266.73   366.6 2251.31   386.4 2250.55   388.2 2250.65
   396.3 2251.09   403.2 2253.36   435.9 2264.99   445.8 2266.17   475.5 2265.64
   495.4    2267   575.1 2277.68     595 2282.75     635 2297.89     655 2308.83
   664.9 2310.73   674.9 2315.31   744.8 2361.75   754.8 2367.16   764.8 2367.42
   794.7 2385.13   814.7 2391.46   854.6 2401.59   874.6 2403.76   894.6 2409.34
#Mann= 3 , 0 , 0
       0      .1       0   388.2    .045       0   403.2      .1       0
Bank Sta=388.2,403.2
XS Rating Curve= 0 ,0
Exp/Cntr=0.3,0.1

Type RM Length L Ch R = 1 ,1153.3  ,170,169.5,169.1
XS GIS Cut Line= 2
     1904654.136       262219.71     1904804.385      261548.485
#Sta/Elev= 30
       0 2269.94      10  2267.8    19.9 2266.54   119.6 2265.96   129.6  2265.2
   139.6 2265.15   219.3 2260.61   229.3  2260.5   259.2 2258.04     319 2251.78
   338.9 2250.76   358.9 2249.05   378.8  2248.7   380.6  2248.7   395.6 2248.81
   398.8 2248.86   408.7 2250.85   418.7  2254.8   428.6 2256.14   458.6 2267.57
   508.4 2287.73   518.4 2288.21   558.2 2305.82   568.2 2310.01   578.2 2313.51
   588.2 2315.84   598.1 2316.63     628 2315.06   657.9 2317.13   687.8 2320.08
#Mann= 3 , 0 , 0
       0     .06       0   380.6    .045       0   395.6      .1       0
Bank Sta=380.6,395.6
XS Rating Curve= 0 ,0
Exp/Cntr=0.3,0.1

Type RM Length L Ch R = 1 ,984.2   ,424.9,437,449.1
XS GIS Cut Line= 3
     1904795.192      262382.768     1904905.641      261834.287
     1904897.475      261698.735
#Sta/Elev= 30
       0 2306.13      10 2304.71      20 2304.42      30 2302.46      60 2295.43
    79.9 2289.51    99.9  2284.3   109.9 2283.82   169.8 2270.03   189.8 2266.37
   249.8 2262.48   259.8 2262.44   299.7 2264.43   319.7  2263.9   379.6 2257.02
   399.6 2255.45   439.6 2249.72   449.6  2248.8   459.6  2248.7   464.9 2248.71
   479.9 2248.85   489.6 2249.17   499.6 2253.53   509.5 2260.26   549.5 2278.57
   559.5 2281.56   569.2 2282.91   578.9 2283.19   637.1 2282.75   695.3 2285.17
#Mann= 3 , 0 , 0
       0     .06       0   464.9    .045       0   479.9      .1       0
Bank Sta=464.9,479.9
XS Rating Curve= 0 ,0
Exp/Cntr=0.3,0.1

Type RM Length L Ch R = 1 ,546.5   ,279.9,267.3,251.9
XS GIS Cut Line= 3
     1904941.253       262475.56     1905251.868      262138.052
     1905323.727      261847.352
#Sta/Elev= 30
       0 2309.96    29.9 2308.55    49.9 2304.69   119.7 2282.75   139.6 2279.32
   169.5 2268.48   189.5 2263.34   249.3 2255.36   269.2 2253.73   289.2 2251.05
   385.8 2245.75   398.9  2245.6   400.8 2245.63   468.7 2250.84   488.6 2256.88
   508.6 2260.58   518.6 2263.51   528.6 2264.28   538.5 2263.01   568.5 2253.55
   578.5 2253.39   588.4 2255.75   598.4 2256.28   628.4    2266   648.3 2270.71
   668.3 2274.32   678.3  2275.4   698.2 2275.43   728.2    2274   758.1 2273.85
#Mann= 3 , 0 , 0
       0      .1       0   385.8    .045       0   400.8      .1       0
Bank Sta=385.8,400.8
XS Rating Curve= 0 ,0
Exp/Cntr=0.3,0.1

Type RM Length L Ch R = 1 ,280     ,277.4,279.1,280.8
XS GIS Cut Line= 3
     1905169.895      262805.801     1905290.529      262665.471
     1905531.798       261702.86
#Sta/Elev= 30
       0 2353.78    19.5 2347.79    68.2  2337.2   204.9 2310.48   274.4 2288.32
   294.2 2283.95   314.1 2275.86   333.9 2270.93   383.5 2263.14   443.1 2250.88
   505.8 2246.39   520.8 2245.63   522.5  2245.6     582 2245.76   720.9  2251.9
   760.6  2260.7   790.4 2264.16   810.3 2262.96     850 2254.12   889.6  2254.1
   919.4 2258.73   949.2 2269.79   959.1 2270.43     979 2277.56   998.8 2279.98
  1018.7 2278.25  1038.5 2273.89  1127.8 2264.22  1147.7 2268.09  1177.4 2270.62
#Mann= 3 , 0 , 0
       0      .1       0   505.8    .045       0   520.8      .1       0
Bank Sta=505.8,520.8
XS Rating Curve= 0 ,0
Exp/Cntr=0.3,0.1

Chan Stop Cuts=-1
Use User Specified Reach Order=0
Composite Channel Slope=5